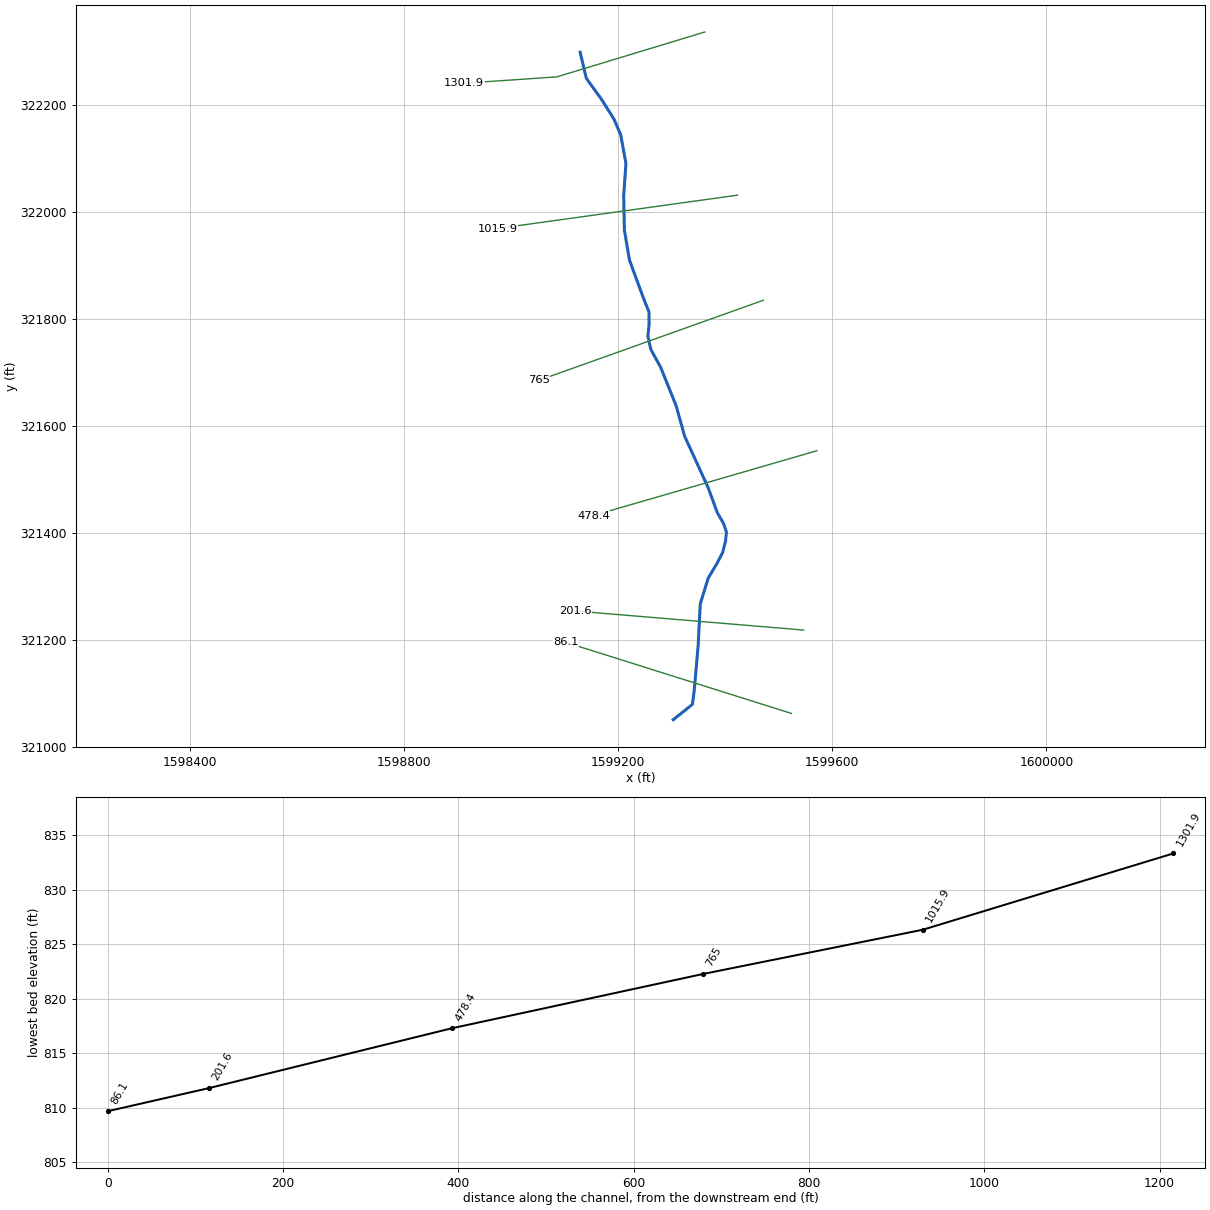
--- dnbrnch.prj (project) ---

Proj Title=dnbrnch
Current Plan=p01
Default Exp/Contr=0,0
English Units
Geom File=g01
Flow File=f01
Plan File=p01
BEGIN DESCRIPTION:
END DESCRIPTION:
DSS Export Rating Curves= 0
DSS Export Rating Curve Sorted= 0
DSS Export Volume Flow Curves= 0
DXF OffsetX= 0
DXF OffsetY= 0
DXF ScaleX= 0
DXF ScaleY= 0

--- dnbrnch.p01 (plan) ---

Plan Title=Approximate Study - 100yr
Program Version=4.00
Geom File=g01
Flow File=f01
Subcritical Flow
K Sum by GR= 0
Std Step Tol= 0.01
Critical Tol= 0.01
Num of Std Step Trials= 20
Max Error Tol= 0.3
Flow Tol Ratio= 0.001
Split Flow NTrial= 30
Split Flow Tol= 0.02
Split Flow Ratio= 0.02
Log Output Level= 0
Friction Slope Method= 1
Unsteady Friction Slope Method= 2
Unsteady Bridges Friction Slope Method= 1
Parabolic Critical Depth
Global Vel Dist= 0 , 0 , 0
Global Log Level= 0
CheckData=True
Encroach Param=-1 ,0,0, 0
Run HTab= 0
Run UNet= 0
Run PostProcess= 0
Run WQNet= 0
UNET Theta= 0
UNET Theta Warmup= 0
UNET ZTol= 0
UNET ZSATol= 0
UNET MxIter= 0
UNET MaxInSteps= 0
UNET DtIC= 0
UNET DtMin= 0
UNET MaxCRTS= 0
UNET WFStab= 0
UNET SFStab= 0
UNET WFX= 1
UNET SFX= 1
UNET DSS MLevel= 1
UNET DZMax Abort= 0
UNET Convert EG Bridges= 0
UNET Use Existing IB Tables= 0
UNET Froude Reduction=False
UNET Froude Limit= 0
UNET Froude Power= 0
UNET Time Slicing=0,0, 5
Write IC File= 0
Echo Input=False
Echo Output=False
Write Detailed= 0
Detailed Automatic Start=False, 0
WQ ULTIMATE=-1
WQ Max Comp Step=1HOUR
WQ Output Interval=15MIN
WQ Output Selected Increments= 0
WQ Output face flow=0
WQ Output face velocity=0
WQ Output face area=0
WQ Output face dispersion=0
WQ Output cell volume=0
WQ Output cell surface area=0
WQ Output cell continuity=0
WQ Output face conc=0
WQ Output face dconc_dx=0
WQ Output face courant=0
WQ Output face peclet=0
WQ Output face adv mass=0
WQ Output face disp mass=0
WQ Output cell mass=0
WQ Output cell source sink temp=0
WQ Output cell source sink nsm=0
WQ Output MaxMinRange=-1
WQ Daily Max Min Mean=-1
WQ Daily Range=0
WQ Daily Time=0
WQ Create Restart=0
WQ Fixed Restart=0
WQ System Summary=False
Sorting and Armoring Iterations= 10
XS Update Threshold= 0.02
Hydraulics Update Threshold= 0.02
Energy Slope Method= 1
Volume Change Method= 0
XS Weighting Method= 0
Number of US Weighted Cross Sections= 1
Number of DS Weighted Cross Sections= 1
Upstream XS Weight=0.25
Main XS Weight=0.5
Downstream XS Weight=0.25
Number of DS XS's Weighted with US Boundary= 1
Upstream Boundary Weight= 1
Weight of XSs Associated with US Boundary= 0
Number of US XS's Weighted with DS Boundary= 1
Downstream Boundary Weight= 0.5
Weight of XSs Associated with DS Boundary= 0.5
Sediment Output Level= 4
Mass or Volume Output= 0
Output Increment Type= 1
Profile and TS Output Increment= 10
XS Output Flag= 0
XS Output Increment= 10
Disregard all LS=0
Disregard all Conn=0
Disregard all Breaches=0
Disregard all Pumps=0

--- dnbrnch.f01 (steady flow) ---

Flow Title=USGS Regression Equation
Program Version=4.00
Number of Profiles= 1
Profile Names=P100yr
River Rch & RM=dnbrnch,Main            ,1301.9
     368
River Rch & RM=dnbrnch,Main            ,201.6
     387
Boundary for River Rch & Prof#=dnbrnch,Main            , 1
Up Type= 0
Dn Type= 3
Dn Slope=0.018507
DSS Import GetInterval= 0
DSS Import GetPeak= 0
DSS Import FillOption= 0

--- dnbrnch.g01 (geometry) ---

Geom Title=USGS 3m DEM
Program Version=4.00

River Reach=dnbrnch         ,Main
Reach XY= 30
     1599128.811      322298.209     1599140.474       322249.27
       1599168.3      322210.853     1599191.882      322173.532
     1599204.728      322143.624     1599214.442      322090.195
     1599210.229      322030.366     1599211.425      321966.248
     1599221.095      321909.645     1599245.765      321842.396
     1599257.547      321812.503     1599257.594        321787.9
     1599255.475        321767.6     1599260.846      321743.046
     1599279.019      321709.951     1599307.984      321638.369
     1599324.077      321580.761     1599368.043      321484.615
     1599385.204      321437.676     1599396.973      321417.368
     1599402.316       321401.36     1599400.227      321383.197
     1599394.914       321362.88      1599384.23      321342.576
     1599368.279      321315.813      1599353.34       321267.73
     1599349.234       321187.57     1599341.841      321104.219
     1599338.647      321079.661     1599302.801      321050.959

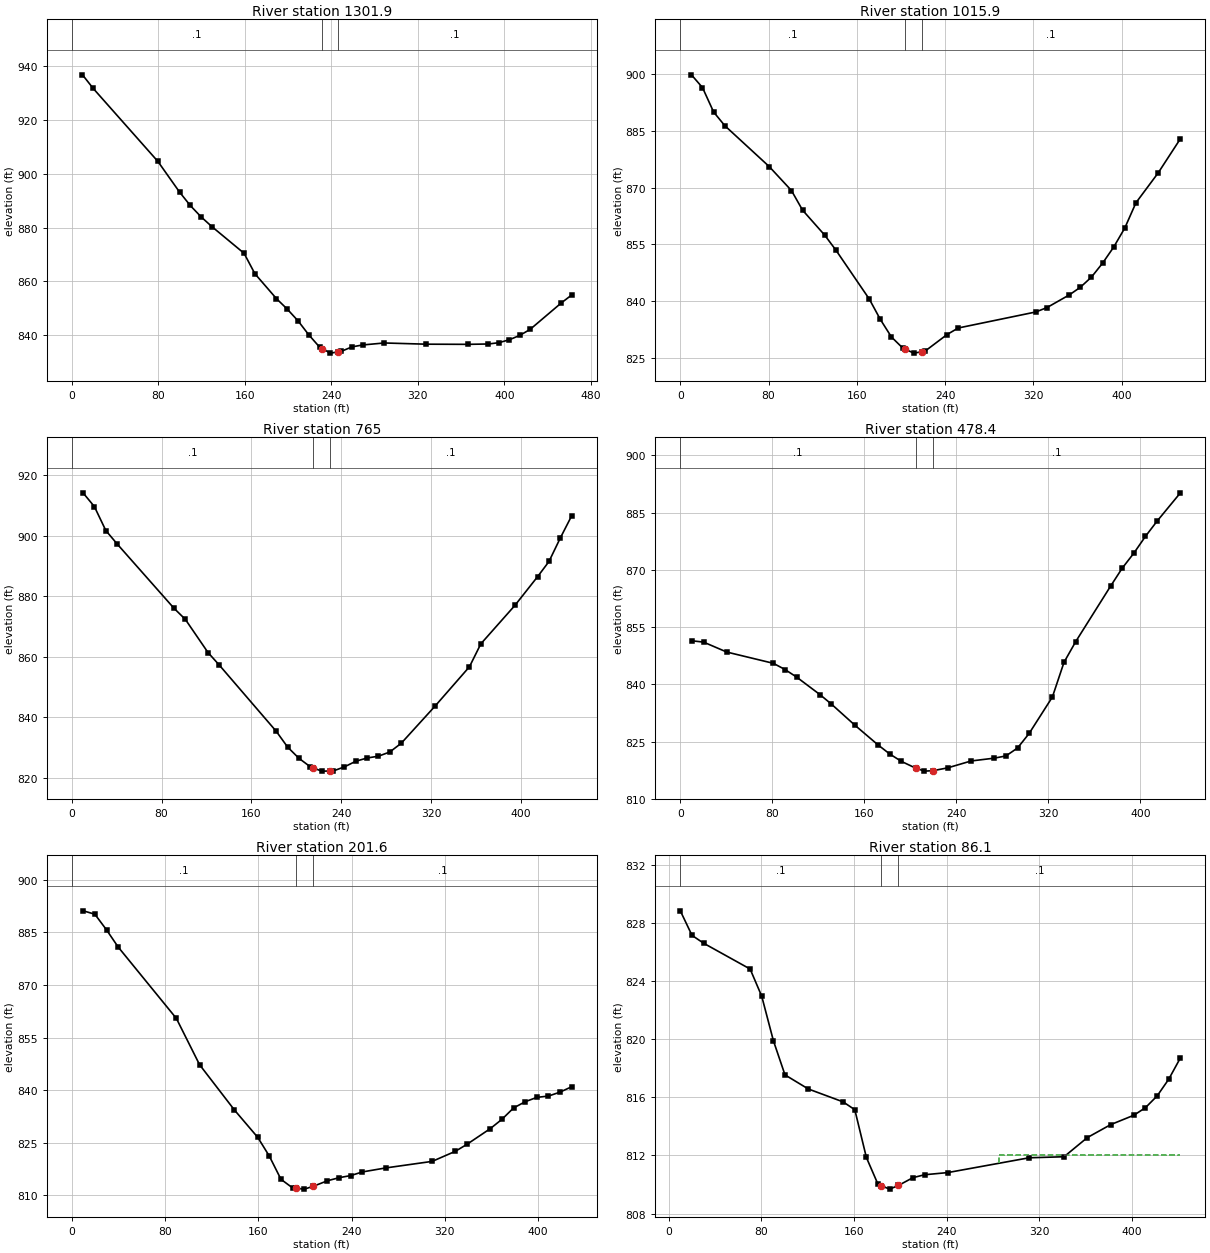
Type RM Length L Ch R = 1 ,1301.9  ,289.4,286,282.5
XS GIS Cut Line= 3
     1599361.812      322336.002     1599085.252      322252.127
     1598912.213      322240.301
#Sta/Elev= 30
      10   936.9    19.9  931.84    79.7  904.68    99.7  893.29   109.6  888.29
   119.6  884.06   129.6  880.42   159.4  870.48   169.4  862.88   189.3  853.62
   199.3  849.71   209.3  845.34   219.2  840.15   229.2  835.57   231.7     835
   239.2  833.32   246.7  833.79   249.1  833.95   259.1  835.64   269.1  836.36
     289   837.1   327.5  836.65   366.1  836.59   385.4  836.72     395  837.21
   404.6  838.29   414.3  839.91   423.9  842.16   452.8  852.03   462.4  854.98
#Mann= 3 , 0 , 0
       0      .1       0   231.7    .045       0   246.7      .1       0
Bank Sta=231.7,246.7
XS Rating Curve= 0 ,0
Exp/Cntr=0.3,0.1

Type RM Length L Ch R = 1 ,1015.9  ,246.3,250.9,255.5
XS GIS Cut Line= 2
     1599423.018      322031.105     1598974.175      321968.766
#Sta/Elev= 30
    10.1  899.79    20.1  896.42    30.2  889.97    40.3  886.37    80.6  875.56
   100.7  869.25   110.8  864.06   130.9  857.45     141  853.51   171.2  840.62
   181.3   835.2   191.3  830.59   201.4  827.71     204  827.35   211.5  826.32
     219  826.67   221.5  826.78   241.7  831.22   251.8  832.95   322.2  837.19
   332.3  838.35   352.5  841.69   362.5   843.7   372.6   846.4   382.7  850.08
   392.7   854.3   402.8  859.35   412.9  866.01     433  873.88   453.2  882.92
#Mann= 3 , 0 , 0
       0      .1       0     204    .045       0     219      .1       0
Bank Sta=204,219
XS Rating Curve= 0 ,0
Exp/Cntr=0.3,0.1

Type RM Length L Ch R = 1 ,765     ,287.9,286.6,285.2
XS GIS Cut Line= 2
     1599471.124      321834.697     1599051.749      321685.082
#Sta/Elev= 30
    10.1  914.22    20.2  909.69    30.4  901.77    40.5  897.32    91.1  876.08
   101.2  872.41   121.4  861.45   131.6  857.23   182.2   835.4   192.3   830.2
   202.4  826.49   212.5  823.69   215.1  823.32   222.6  822.26   230.1  822.29
   232.8   822.3   242.9  823.67     253  825.53   263.1   826.6   273.2   827.2
   283.3  828.59   293.5  831.48   323.8  843.84   354.2  856.75   364.3   864.3
   394.7  877.03   414.9  886.53     425  891.53   435.1   899.3   445.3  906.69
#Mann= 3 , 0 , 0
       0      .1       0   215.1    .045       0   230.1      .1       0
Bank Sta=215.1,230.1
XS Rating Curve= 0 ,0
Exp/Cntr=0.3,0.1

Type RM Length L Ch R = 1 ,478.4   ,285.1,276.8,268.5
XS GIS Cut Line= 2
     1599571.196      321553.516      1599153.62      321432.509
#Sta/Elev= 30
    10.1  851.42    20.2  851.08    40.4  848.47    80.9  845.52      91   843.9
   101.1  841.92   121.3  837.35   131.4  834.83   151.7  829.33   171.9  824.15
     182  821.79   192.1  819.85   204.8  818.04   212.3  817.28   219.8   817.4
   232.5  818.14   252.8  819.94     273  820.68   283.1  821.26   293.2  823.34
   303.3  827.16   323.5   836.7   333.6  845.79   343.8  851.22   374.1  865.74
   384.2  870.44   394.3  874.37   404.4  878.77   414.5  882.76   434.8  890.18
#Mann= 3 , 0 , 0
       0      .1       0   204.8    .045       0   219.8      .1       0
Bank Sta=204.8,219.8
XS Rating Curve= 0 ,0
Exp/Cntr=0.3,0.1

Type RM Length L Ch R = 1 ,201.6   ,120.6,115.5,110.4
XS GIS Cut Line= 2
     1599546.715      321218.475     1599119.346      321254.147
#Sta/Elev= 30
      10  891.13    19.9  890.16    29.9   885.7    39.9   880.8    89.8  860.46
   109.7  847.26   139.6  834.35   159.6  826.55   169.5  821.22   179.5   814.6
   189.5  812.14     192  812.06   199.5   811.8     207  812.58   219.4  814.19
   229.4  815.06   239.4  815.67   249.3   816.7   269.3  817.84   309.2  819.71
   329.1  822.59   339.1  824.59     359  829.04     369   831.7     379  834.94
     389  836.72   398.9  837.95   408.9  838.33   418.9  839.46   428.9     841
#Mann= 3 , 0 , 0
       0      .1       0     192    .045       0     207      .1       0
Bank Sta=192,207
XS Rating Curve= 0 ,0
Exp/Cntr=0.3,0.1

Type RM Length L Ch R = 1 ,86.1    ,100.2,86.1,72
XS GIS Cut Line= 2
     1599523.517      321062.766     1599102.064      321195.547
#Sta/Elev= 27
      10  828.85    20.1  827.16    30.1  826.62    70.3  824.84    80.3  822.97
    90.4   819.9   100.4  817.55   120.5  816.58   150.6  815.69   160.7  815.15
   170.7  811.86   180.8     810   183.3  809.92   190.8  809.68   198.3  809.93
   210.9  810.47   220.9  810.67     241  810.82   311.3  811.84   341.4  811.91
   361.5  813.23   381.6  814.12   401.7  814.77   411.7  815.29   421.8   816.1
   431.8  817.25   441.9  818.72
#Mann= 3 , 0 , 0
      10      .1       0   183.3    .045       0   198.3      .1       0
#XS Ineff= 2 , 0
       0                     285       0     812
Permanent Ineff=
       F       F
Bank Sta=183.3,198.3
XS Rating Curve= 0 ,0
Exp/Cntr=0.3,0.1

Chan Stop Cuts=-1
Use User Specified Reach Order=0